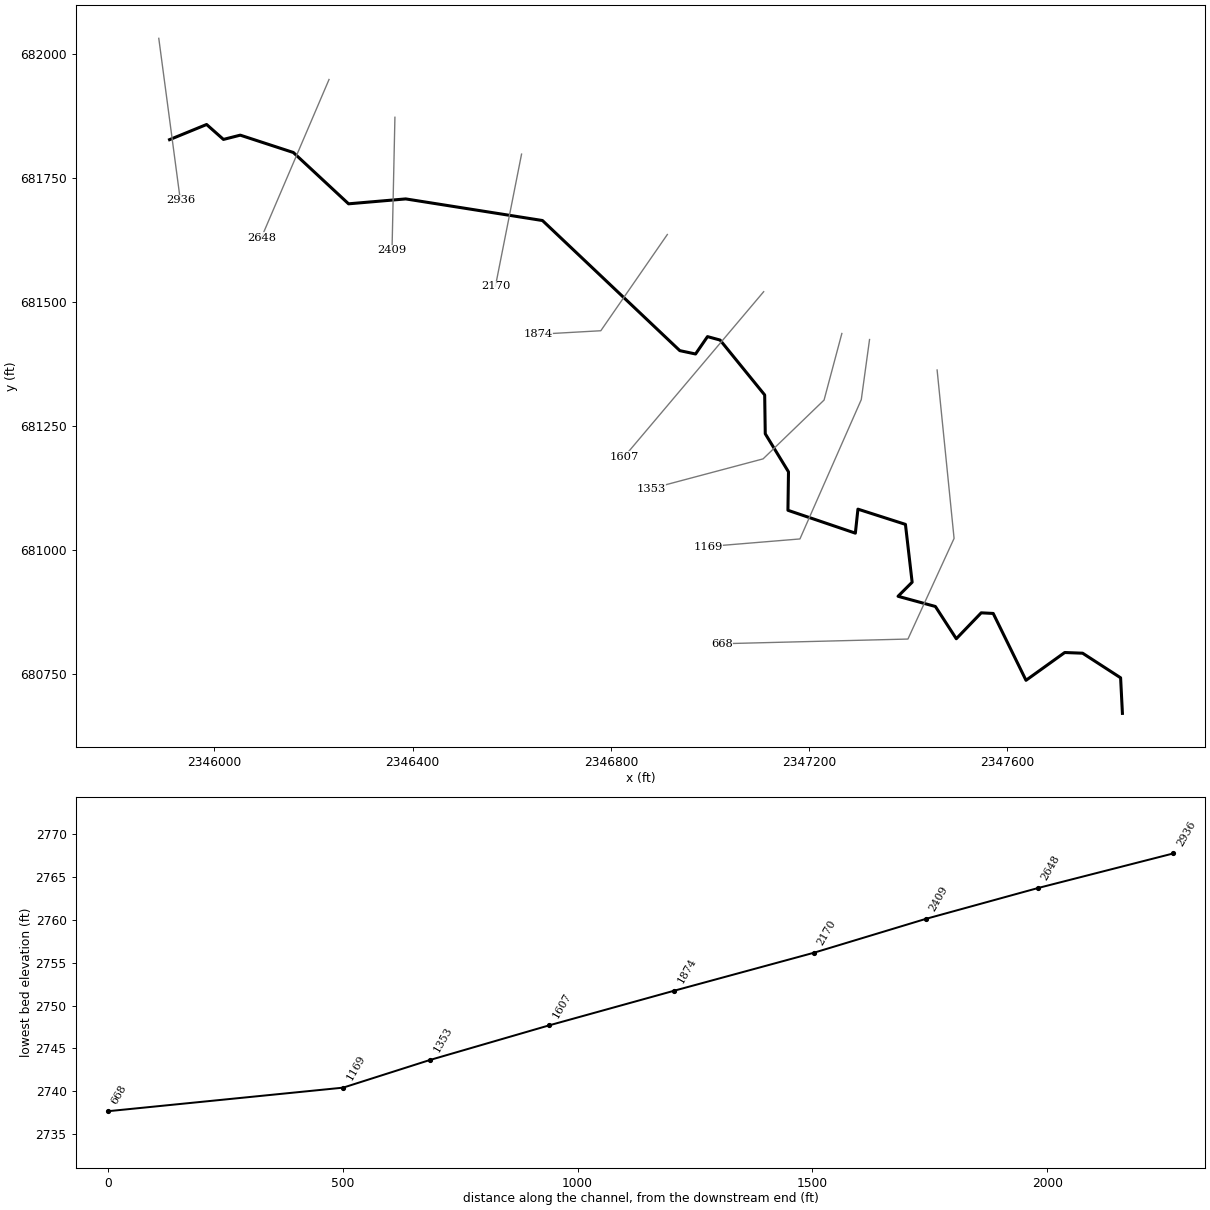
--- GAPRN.prj (project) ---

Proj Title=GAPRN
Current Plan=p01
Default Exp/Contr=0,0
English Units
Geom File=g01
Flow File=f01
Plan File=p01
BEGIN DESCRIPTION:
----------MODEL BY WOOD PLC 2022----------
AFH study
Randolph County, WV
HEC-RAS Version: RAS 6.2
Vertical Datum: NAVD88
Projection: NAD 1983 StatePlane West Virginia S FIPS 4702 (US Feet)
Terrain: 1-meter LIDAR (FEMA Region III 3DEP collected 2016-2018)
Land Use: 2019 NLCD
Hydrologic Method:
WV SIR2010-5033 regression equations
Additional Model Notes:
None
END DESCRIPTION:
DSS File=dss
DSS Export Rating Curves= 0
DSS Export Rating Curve Sorted= 0
DSS Export Volume Flow Curves= 0
DXF OffsetX= 0
DXF OffsetY= 0
DXF ScaleX= 0
DXF ScaleY= 0

--- GAPRN.p01 (plan) ---

Plan Title=Floodplain
Program Version=6.20
Short Identifier=Floodplain
Geom File=g01
Flow File=f01
Subcritical Flow
K Sum by GR= 0
Std Step Tol= 0.01
Critical Tol= 0.01
Num of Std Step Trials= 20
Max Error Tol= 0.3
Flow Tol Ratio= 0.001
Split Flow NTrial= 30
Split Flow Tol= 0.02
Split Flow Ratio= 0.02
Log Output Level= 0
Friction Slope Method= 1
Unsteady Friction Slope Method= 2
Unsteady Bridges Friction Slope Method= 1
Parabolic Critical Depth
Global Vel Dist= 0 , 0 , 0
Global Log Level= 0
CheckData=True
Encroach Param=-1 ,0,0, 0
Computation Interval=0.1SEC
Output Interval=1SEC
Instantaneous Interval=Max Profile
Mapping Interval=1HOUR
Computation Time Step Use Courant=        0
Computation Time Step Use Time Series=    0
Computation Time Step Count To Double=0
Computation Time Step Max Doubling=0
Computation Time Step Max Halving=0
Computation Time Step Residence Courant=0
Run HTab= 0
Run UNet= 0
Run Sediment= 0
Run PostProcess= 0
Run WQNet= 0
Run RASMapper=-1
UNET Theta= 0
UNET Theta Warmup= 0
UNET ZTol= 0
UNET ZSATol= 0
UNET MxIter= 0
UNET Max Iter WO Improvement= 0
UNET MaxInSteps= 0
UNET DtIC= 0
UNET DtMin= 0
UNET MaxCRTS= 0
UNET WFStab= 0
UNET SFStab= 0
UNET WFX= 1
UNET SFX= 1
UNET Gravity=32.174
UNET 1D Methodology=Finite Difference
UNET DSS MLevel= 1
UNET Pardiso=0
UNET DZMax Abort= 0
UNET Use Existing IB Tables= 0
UNET Froude Reduction=False
UNET Froude Limit= 0
UNET Froude Power= 0
UNET D1 Cores= 0
UNET WindReference=Eulerian
UNET WindDragFormulation=Hsu (1988)
UNET D2 Coriolis=0
UNET D2 Cores= 0
UNET D2 Theta= 1
UNET D2 Theta Warmup= 1
UNET D2 Z Tol= 0.01
UNET D2 Volume Tol= 0.01
UNET D2 Max Iterations= 20
UNET D2 Equation= 0
UNET D2 RampUpFraction=0.1
UNET D2 TimeSlices= 1
UNET D2 Turbulence Formulation=Non-Conservative (original)
UNET D2 Eddy Viscosity=0.3
UNET D2 Transverse Eddy Viscosity=0.1
UNET D2 Smagorinsky Mixing=0
UNET D2 BCVolumeCheck=0
UNET D2 Cores=0
UNET D2 SolverType=PARDISO (Direct)
UNET D2 Minimum Iterations= 2147483647
UNET D2 Maximum Iterations= 2147483647
UNET D2 Restart Number= 10
UNET D2 Relaxation Coeff=1.3
UNET D2 SOR Precondition Iterations= 10
UNET D2 ILUT Maximum Fill= 8
UNET D2 ILUT Tolerance=1E-08
UNET D1D2 MaxIter= 0
UNET D1D2 ZTol=0.01
UNET D1D2 QTol=0.1
UNET D1D2 MinQTol=1
DSS File=dss
Write IC File= 0
Write IC File at Fixed DateTime=0
Write IC File at Sim End=0
Echo Input=False
Echo Parameters=False
Echo Output=False
Write Detailed= 0
HDF Write Warmup=0
HDF Write Time Slices=0
HDF Flush=0
HDF Compression= 1
HDF Chunk Size= 1
HDF Spatial Parts= 1
HDF Use Max Rows=0
HDF Fixed Rows= 1
Calibration Method= 0
Calibration Iterations= 20
Calibration Max Change=0.05
Calibration Tolerance=0.2
Calibration Maximum=1.5
Calibration Minimum=0.5
Calibration Optimization Method= 1
WQ AD Non Conservative
WQ ULTIMATE=-1
WQ Max Comp Step=1HOUR
WQ Output Interval=15MIN
WQ Output Selected Increments= 0
WQ Output face flow=0
WQ Output face velocity=0
WQ Output face area=0
WQ Output face dispersion=0
WQ Output cell volume=0
WQ Output cell surface area=0
WQ Output cell continuity=0
WQ Output cumulative cell continuity=0
WQ Output face conc=0
WQ Output face dconc_dx=0
WQ Output face courant=0
WQ Output face peclet=0
WQ Output face adv mass=0
WQ Output face disp mass=0
WQ Output cell mass=0
WQ Output cell source sink temp=0
WQ Output nsm pathways=0
WQ Output nsm derived pathways=0
WQ Create Restart=0
WQ Fixed Restart=0
WQ System Summary=0
WQ Write To DSS=0
Sorting and Armoring Iterations= 10
XS Update Threshold= 0.02
Bed Roughness Predictor= 0
Hydraulics Update Threshold= 0.02
Energy Slope Method= 1
Volume Change Method= 1
Sediment Retention Method= 0
Sediment TS Multiplier= 1
Warm Up Method= 0
XS Weighting Method= 0
Number of US Weighted Cross Sections= 1
Number of DS Weighted Cross Sections= 1
Upstream XS Weight=0
Main XS Weight=1
Downstream XS Weight=0
Number of DS XS's Weighted with US Boundary= 1
Upstream Boundary Weight= 1
Weight of XSs Associated with US Boundary= 0
Number of US XS's Weighted with DS Boundary= 1
Downstream Boundary Weight= 0.5
Weight of XSs Associated with DS Boundary= 0.5
Percentile Method= 0
Sediment Output Level= 3
Mass or Volume Output= 0
Output Increment Type= 1
Profile and TS Output Increment= 1
Transport Output Increment 1
XS Output Flag= 0
XS Output Increment= 10
Read HDF5 Sediment Hotstart= 0
Sediment Hotstart Type= 0
Write Gradation File= 0
Read Gradation Hotstart= 0
Write HDF5 File= 1
Write Binary Output= 1
Write DSS Sediment File= 0
DSS Sediment Output Type= 1
SV Curve= 0
Specific Gage Flag= 0
Subcell Erosion Methods= 0
Subcell Deposition Methods= 0
Advection Scheme= 1
Matrix Solver= 0
Implicit Weighting Factor= 1
Maximum Outer Loop Convergence Iterations= 5
Convergence Maximum Absolute= 0.001
Convergence RMSE= 0.0001
Grain Fractions Max Abs Error= 0.001
Max Subgrid Regions= 1
Max Subgrid Length Scale= 3.402823E+38
Initial Layer Thickness= 3.402823E+38
Min Layer Thickness= 3.402823E+38
Max Layer Thickness= 3.402823E+38
Number of Layers= 5

--- GAPRN.f01 (steady flow) ---

Flow Title=Flow
Program Version=6.20
Number of Profiles= 1
Profile Names=P100yr
River Rch & RM=GAPRN,Main            ,2936
     359
Boundary for River Rch & Prof#=GAPRN,Main            , 1
Up Type= 0
Dn Type= 3
Dn Slope=0.00547
DSS Import GetInterval= 0
DSS Import GetPeak= 0
DSS Import FillOption= 0

--- GAPRN.g01 (geometry) ---

Geom Title=Geometry
Program Version=6.20

River Reach=GAPRN           ,Main
Reach XY= 30
2345909.75019808681827.3836769162345984.49100001681857.981000006
     2346018.478 681827.865000012346052.39300002681836.456000015
2346159.51200002681801.4660000062346270.86500002681697.941000015
2346386.23000003681707.8350000082346662.08199999681664.231999993
2346939.16500002681401.7319999932346970.93600003681394.960999995
2346995.03200002681430.0160000032347020.41500004 681423.08600001
2347110.39500004681312.3190000212347111.56100002681234.023000002
2347158.43600003      681157.1842347157.31900001681079.640000016
2347293.33199999681033.5020000042347298.54000004681081.940000013
2347394.37400003681051.2109999952347407.88900001680934.548000008
2347379.43700001680906.1400000012347454.79000004 680885.58600001
2347496.97799999680820.4820000082347547.25700003      680872.772
2347571.45700003680871.5230000172347637.60300002680736.627000019
2347715.72800002680792.7039999962347751.83900002680791.314999998
 2347828.4599405680741.698920775  2347832.133902680669.918568488

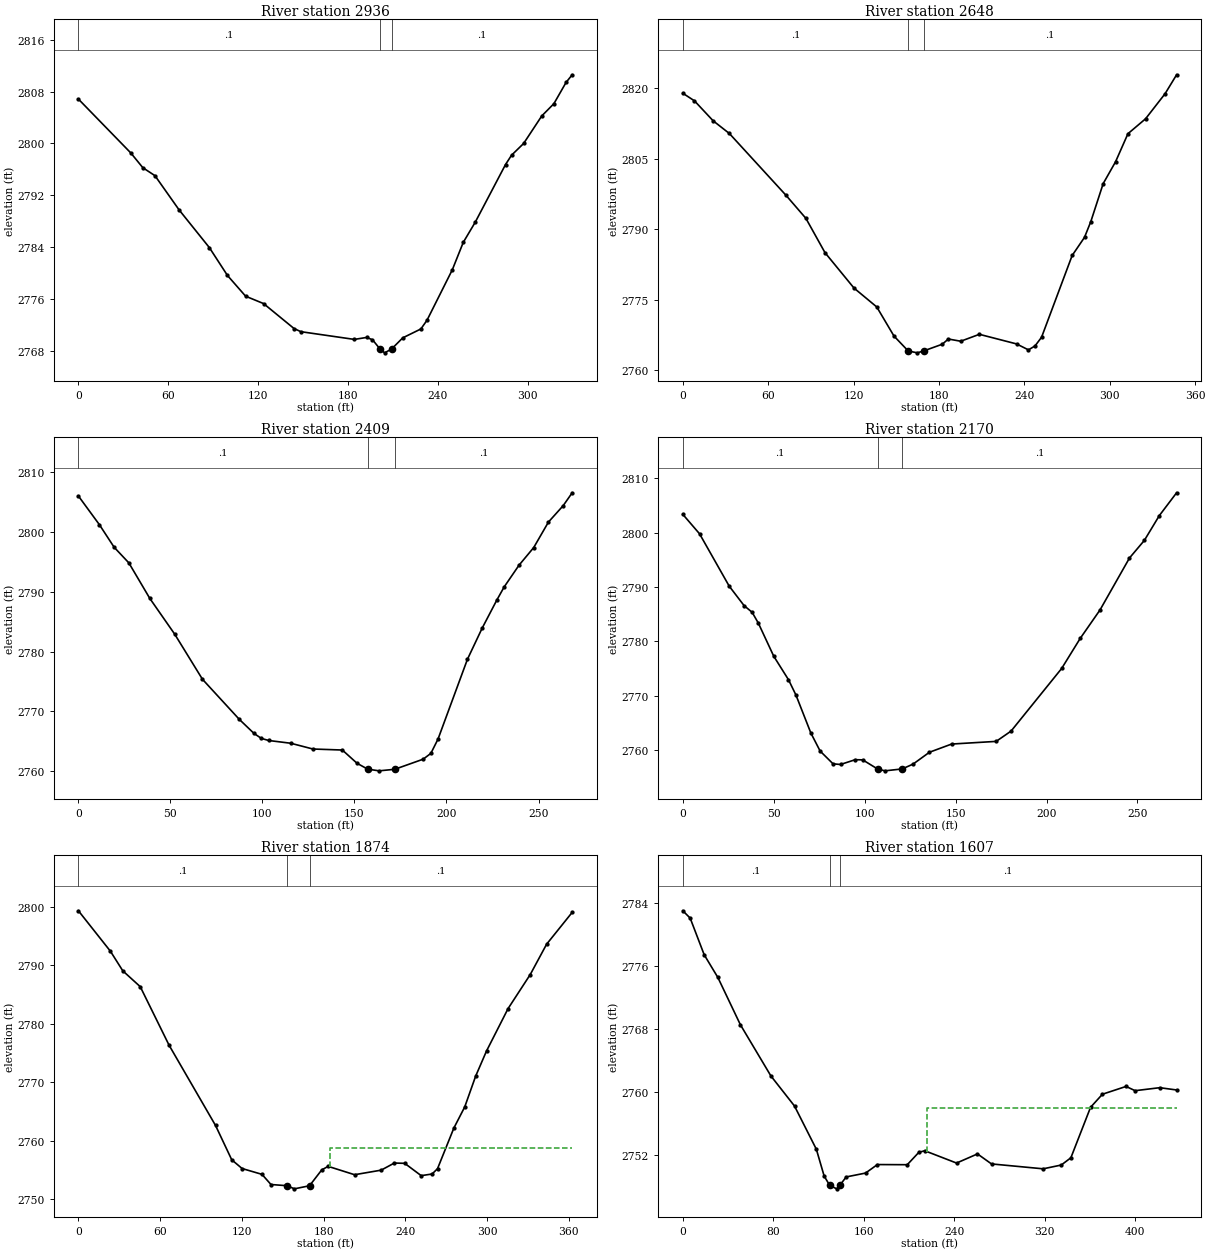
Type RM Length L Ch R = 1 ,2936    ,288.7,287.9,283.9
XS GIS Cut Line= 2
2345888.01412665682031.7985037042345931.48526225681705.117114833
#Sta/Elev= 30
       0 2806.84    34.9 2798.56      43 2796.27    51.1 2795.04    67.2 2789.77
    87.4 2783.96    99.5 2779.66   111.6 2776.47   123.6 2775.33   143.9 2771.49
   148.5    2771   184.2 2769.81   192.3 2770.11   196.3 2769.76   201.4 2768.31
   204.4 2767.74     209 2768.32   216.5 2770.05   228.6 2771.42   232.7 2772.77
   249.6 2780.55   256.9 2784.77   264.9 2787.88   285.1 2796.76   289.1 2798.19
   297.2 2800.01   309.3 2804.25   317.4 2806.14   325.5 2809.41   329.6 2810.59
#Mann= 3, -1 ,  0
       0     0.1       0   201.4   0.045       0     209     0.1       0
Bank Sta=201.4,209
XS Rating Curve= 0 ,0
Exp/Cntr(USF)=0,0
Exp/Cntr=0.3,0.1

Type RM Length L Ch R = 1 ,2648    ,236.9,239.6,242.8
XS GIS Cut Line= 2
2346231.46831209 681948.749279342346095.04591036681629.745142722
#Sta/Elev= 30
       0 2818.94     8.2 2817.32    21.3 2813.08    32.7 2810.38    72.3  2797.3
    86.5 2792.32    99.9 2785.03   120.3 2777.49   136.3 2773.47   148.4 2767.28
  158.38 2764.11   164.8 2763.71   169.2 2764.11   182.3 2765.54   186.6 2766.65
   195.3 2766.18   208.4 2767.65   234.5 2765.61   242.9 2764.34   247.5 2765.18
   252.1 2767.02   273.6 2784.42   282.3 2788.29   286.7 2791.62   295.4 2799.71
   304.1 2804.36   312.8 2810.33   325.2 2813.51   338.9 2818.84     347 2822.87
#Mann= 3, -1 ,  0
       0     0.1       0  158.38   0.045       0   169.2     0.1       0
Bank Sta=158.38,169.2
XS Rating Curve= 0 ,0
Exp/Cntr=0.3,0.1

Type RM Length L Ch R = 1 ,2409    ,239.6,238.4,237.1
XS GIS Cut Line= 2
2346364.41761682681872.5455488112346358.56451119681604.278207388
#Sta/Elev= 30
       0 2805.93    11.4 2801.15    19.4 2797.39    27.4 2794.78    38.8 2788.85
    52.3  2782.9    67.4 2775.37    87.4 2768.69    95.4 2766.34    99.4 2765.51
   103.4 2765.16   115.4  2764.7   127.4 2763.74   143.4 2763.57   151.4 2761.36
   157.22760.379   163.4  2760.1   171.9 2760.36   187.3 2762.04   191.5 2763.01
   195.4  2765.4   211.4 2778.72   219.4 2783.91   227.4 2788.61   231.4  2790.8
   239.4 2794.39   247.4 2797.34   255.4 2801.59   263.4 2804.32   268.3 2806.47
#Mann= 3, -1 ,  0
       0     0.1       0   157.2   0.045       0   171.9     0.1       0
Bank Sta=157.2,171.9
XS Rating Curve= 0 ,0
Exp/Cntr(USF)=0,0
Exp/Cntr=0.3,0.1

Type RM Length L Ch R = 1 ,2170    ,299.6,296.3,294.6
XS GIS Cut Line= 2
2346619.90149812 681798.201788282346567.22354744681531.885482067
#Sta/Elev= 30
       0 2803.35     9.2 2799.77    25.5 2790.14    33.7 2786.55    38.1 2785.33
    41.5 2783.35      50 2777.24    58.1 2772.92    62.2  2770.1    70.4 2763.11
    75.5 2759.79    82.6 2757.44    86.7 2757.32    94.8  2758.2    98.9 2758.17
   107.1 2756.49   111.1 2756.15  120.61  2756.5   126.6 2757.39   135.6 2759.57
   147.8 2761.08   172.3 2761.57   180.5 2763.47   208.3 2774.99   218.5 2780.52
   229.4 2785.76   245.6 2795.32   253.8 2798.57     262 2803.12   271.5 2807.32
#Mann= 3, -1 ,  0
       0     0.1       0   107.1   0.045       0  120.61     0.1       0
Bank Sta=107.1,120.61
XS Rating Curve= 0 ,0
Exp/Cntr(USF)=0,0
Exp/Cntr=0.3,0.1

Type RM Length L Ch R = 1 ,1874    ,264.9,266.9,264.4
XS GIS Cut Line= 3
2346914.00202673681636.0319479012346779.79927876681441.886211665
 2346653.4367694681434.754174855
#Sta/Elev= 30
       0 2799.37    23.5 2792.44    32.6 2789.08    45.4 2786.37    66.6 2776.33
   100.7 2762.59   112.6 2756.71   120.2 2755.22   134.8 2754.22   141.4 2752.48
   153.32752.275   158.6 2751.74  169.71 2752.27   178.7 2754.99   183.4 2755.59
   202.8 2754.16   222.3 2754.94     232 2756.16   239.6 2756.11   251.7    2754
   259.7 2754.28   263.7 2755.19   275.7 2762.15   283.7 2765.78   291.7 2771.04
   299.7 2775.36   315.5 2782.61   331.8 2788.45   343.8 2793.64   362.6  2799.1
#Mann= 3, -1 ,  0
       0     0.1       0   153.3   0.045       0  169.71     0.1       0
#XS Ineff= 2 , 0
                          184.72          2758.7
Permanent Ineff=
       F       F
Bank Sta=153.3,169.71
XS Rating Curve= 0 ,0
Exp/Cntr=0.3,0.1

Type RM Length L Ch R = 1 ,1607    ,253.8,253.9,253.6
XS GIS Cut Line= 2
2347108.37770239681520.6562499962346826.56150534681187.053315881
#Sta/Elev= 30
       0 2782.96     6.5 2782.03    18.9 2777.38      31  2774.5    50.9 2768.51
    77.9 2762.01    98.8 2758.19   118.1 2752.71     125 2749.31   129.82748.158
     136 2747.69   138.9 2748.15   144.5  2749.2   161.6 2749.69   172.1 2750.77
   198.5 2750.75   208.8 2752.33     214 2752.52   242.1 2750.96   260.6 2752.12
     273 2750.85   318.7 2750.23   334.7 2750.71   343.2 2751.63   360.6 2758.03
   371.1 2759.69     392 2760.68     400 2760.14   421.8 2760.52   436.7 2760.23
#Mann= 3, -1 ,  0
       0     0.1       0   129.8   0.045       0   138.9     0.1       0
#XS Ineff= 2 , 0
                          216.26         2757.89
Permanent Ineff=
       F       F
Bank Sta=129.8,138.9
XS Rating Curve= 0 ,0
Exp/Cntr(USF)=0,0
Exp/Cntr=0.3,0.1

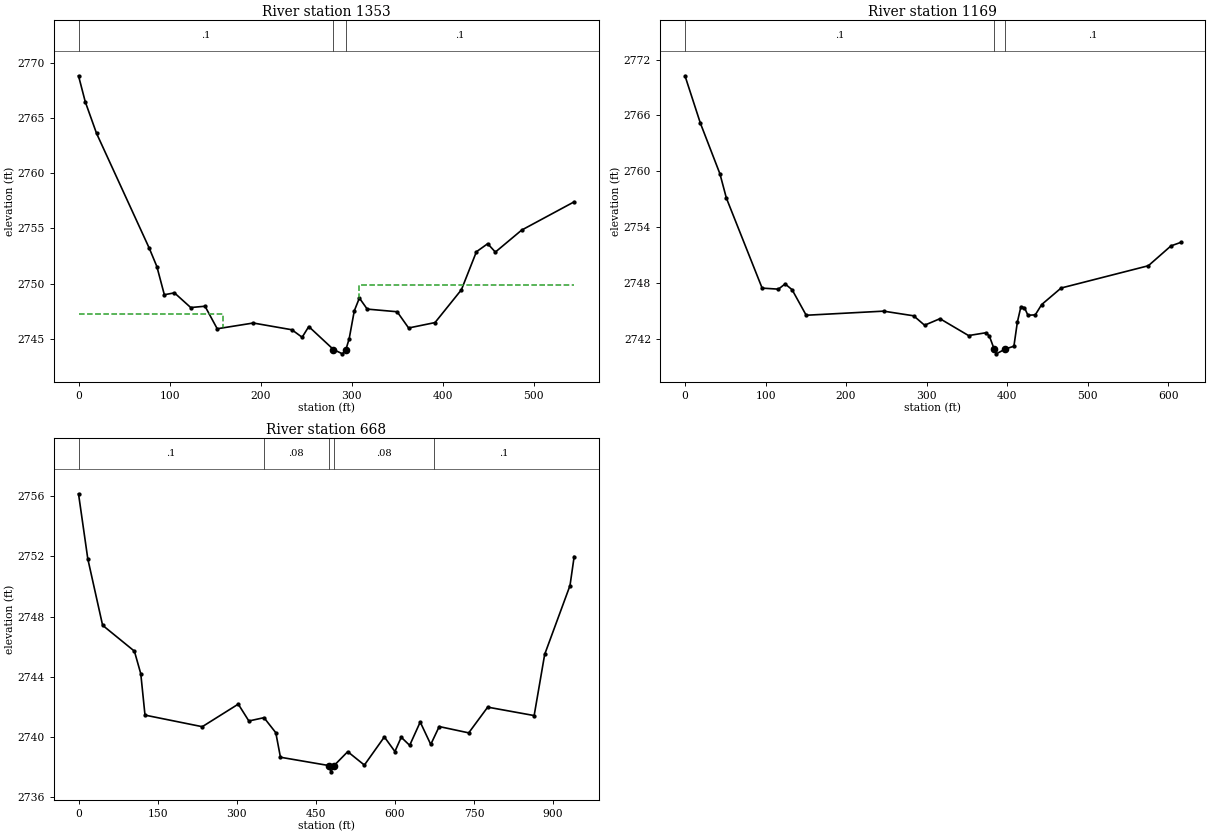
Type RM Length L Ch R = 1 ,1353    ,180.5,184.5,184.1
XS GIS Cut Line= 4
2347266.07445441681436.3220883172347230.21219368681302.036134753
2347107.19555616681183.374068477 2346880.4320332681123.067811851
#Sta/Elev= 30
       0 2768.82     7.4 2766.47    19.8 2763.61    77.8  2753.2    86.1 2751.55
    94.3    2749   105.4 2749.17   123.3 2747.84     139 2747.96   152.4 2745.92
     192 2746.44   234.4 2745.83   245.7 2745.15     253 2746.12  280.14 2744.04
     290 2743.65   293.8 2744.04   297.4 2745.02     303 2747.54   308.6  2748.7
   317.2  2747.7   350.1 2747.46   362.7 2745.99   391.7 2746.48   420.7 2749.45
   437.2 2752.89   449.6 2753.62     458 2752.86   486.9 2754.85   544.6 2757.41
#Mann= 3, -1 ,  0
       0     0.1       0  280.14   0.045       0   293.8     0.1       0
#XS Ineff= 2 , 0
          158.44 2747.28  308.29          2749.9
Permanent Ineff=
       F       F
Bank Sta=280.14,293.8
XS Rating Curve= 0 ,0
Exp/Cntr(USF)=0,0
Exp/Cntr=0.3,0.1

Type RM Length L Ch R = 1 ,1169    ,494.4,501,492.2
XS GIS Cut Line= 4
 2347321.9544669681424.1368485812347305.30526658681302.954029026
2347181.51448618681021.827923984 2346996.2589908681006.515196167
#Sta/Elev= 30
       0 2770.26    19.1 2765.18    43.4 2759.74    51.4 2757.14    95.8 2747.48
     116 2747.37   124.3 2747.93     133 2747.31   150.5 2744.57   246.6 2745.01
   283.9 2744.51   297.5  2743.5   316.6  2744.2   352.1 2742.39   373.4 2742.69
   377.8 2742.36  383.98 2740.92   386.5 2740.43   397.6 2740.94   408.4 2741.25
   412.7 2743.84   417.1 2745.49   421.5 2745.38   425.8 2744.57   434.9 2744.61
   442.9 2745.72     467 2747.49   575.3 2749.88   603.4 2752.01   615.4 2752.38
#Mann= 3, -1 ,  0
       0     0.1       0  383.98   0.045       0   397.6     0.1       0
Bank Sta=383.98,397.6
XS Rating Curve= 0 ,0
Exp/Cntr(USF)=0,0
Exp/Cntr=0.3,0.1

Type RM Length L Ch R = 1 ,668     ,,,
XS GIS Cut Line= 4
2347458.27274487681362.6712600082347492.49982952681022.943059263
 2347399.4139869680819.8698838332347024.24106663 680810.41393705
#Sta/Elev= 30
       0 2756.16    17.6 2751.84    45.7 2747.42     106  2745.7   118.1  2744.2
   126.1 2741.45   234.7 2740.68     303 2742.18   323.1 2741.06   351.8 2741.28
   374.2 2740.28     383 2738.65   474.4  2738.1   478.8 2737.68   484.8  2738.1
   510.6 2739.02   542.2 2738.13   580.1    2740   600.1 2739.03   612.1 2739.98
   628.1 2739.44   648.1 2740.99   668.1  2739.5   684.1 2740.69   740.1 2740.27
   776.1 2741.98   864.2 2741.42   884.2 2745.49   932.2 2750.06   940.1 2751.99
#Mann= 5, -1 ,  0
       0     0.1       0  351.45    0.08       0   474.4   0.045       0
   484.8    0.08       0  674.84     0.1       0
Bank Sta=474.4,484.8
XS Rating Curve= 0 ,0
Exp/Cntr=0.3,0.1
LCMann Table=0

Chan Stop Cuts=-1
Use User Specified Reach Order=0
Composite Channel Slope=5